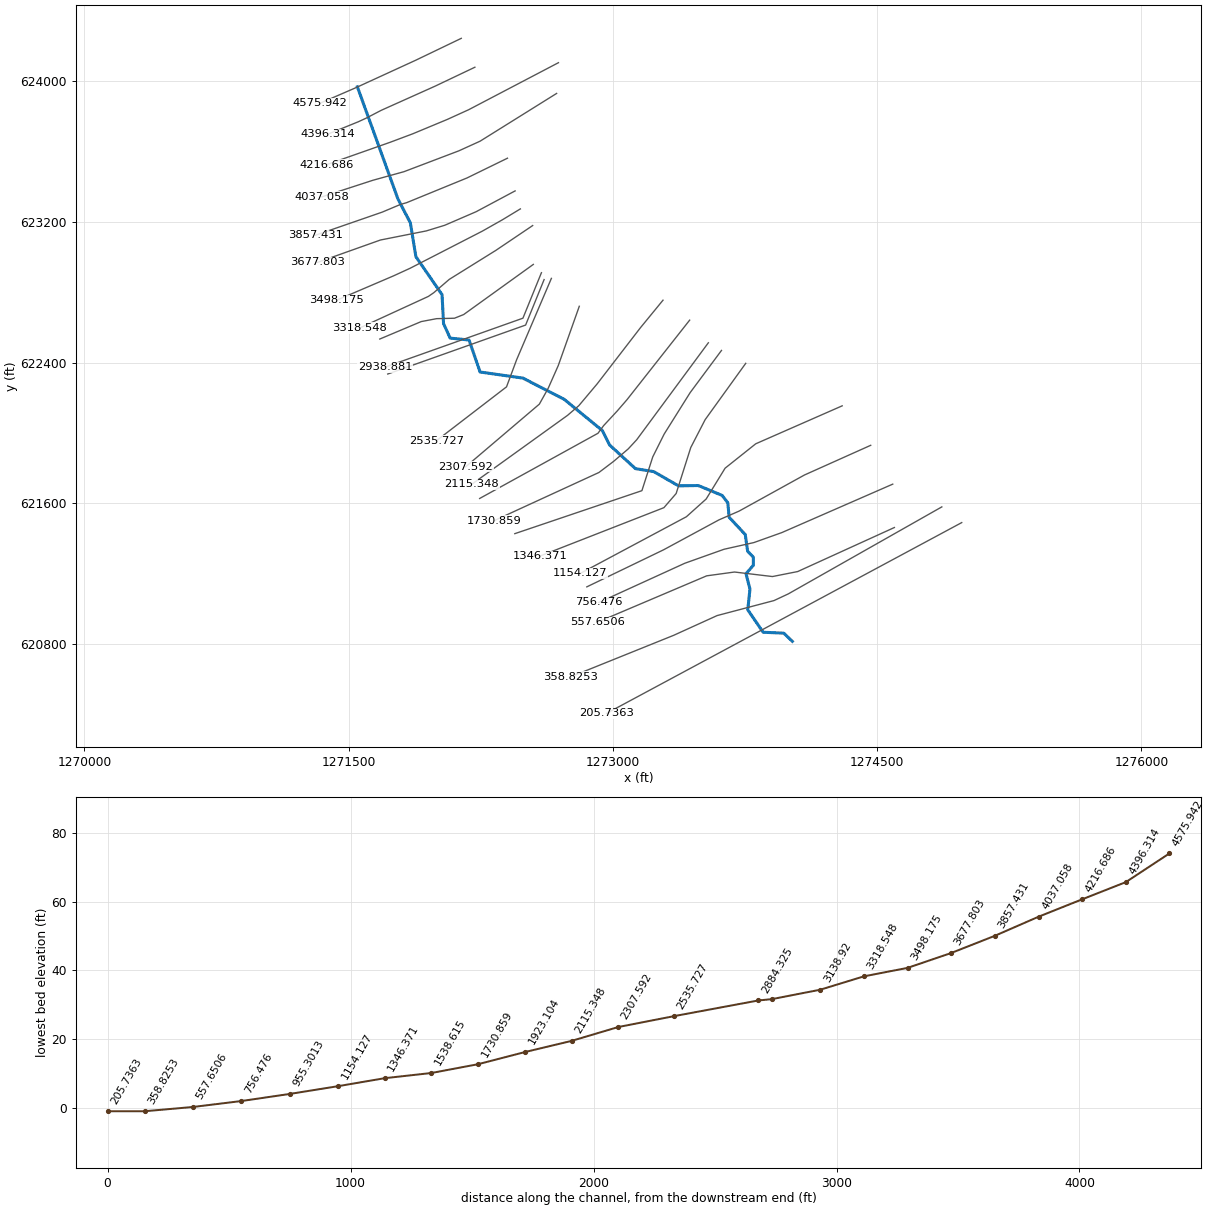
--- 542_ras.prj (project) ---

Proj Title=542
Current Plan=p01
Default Exp/Contr=0.3,0.1
English Units
Geom File=g01
Flow File=f01
Plan File=p01
Y Axis Title=Elevation
X Axis Title(PF)=Main Channel Distance
X Axis Title(XS)=Station
BEGIN DESCRIPTION:
RFD model 542 exported to HEC-RAS
END DESCRIPTION:

--- 542_ras.p01 (plan) ---

Plan Title=Plan 01
Program Version=4.10
Short Identifier=Plan 01
Geom File=g01
Flow File=f01
Subcritical Flow
Calc Critical at every XS
Secant Critical Depth

--- 542_ras.f01 (steady flow) ---

Flow Title=Flow 01
Program Version=5.01
Number of Profiles= 5
Profile Names=10yr,25yr,50yr,100yr,500yr
River Rch & RM=542,24,4575.942
  411.96  496.54  593.35  639.53  760.06
River Rch & RM=542,24,4396.314
  419.01  506.29  605.34   654.1  779.87
River Rch & RM=542,24,4216.686
  424.37  513.72  614.48  665.22  795.05
River Rch & RM=542,24,4037.058
  426.64  516.86  618.35  669.94   801.5
River Rch & RM=542,24,3857.431
  429.63  521.02  623.47  676.18  810.04
River Rch & RM=542,24,3677.803
  443.42  540.23  647.14  705.14  849.81
River Rch & RM=542,24,3498.175
  445.54  543.19  650.79  709.62  855.98
River Rch & RM=542,24,3318.548
  478.16  589.02  707.35  779.39  952.83
River Rch & RM=542,24, 3138.92
  480.68  592.57  711.74  784.84  960.45
River Rch & RM=542,24,2938.881
  481.93  594.33  713.92  787.55  964.24
River Rch & RM=542,24,2884.325
  529.97  662.72  798.58  893.41 1113.75
River Rch & RM=542,24,2535.727
  550.39  692.08     835   939.4 1179.51
River Rch & RM=542,24,2307.592
  553.94  697.19  841.35  947.44 1191.05
River Rch & RM=542,24,2115.348
  560.43  706.56  852.99   962.2 1212.29
River Rch & RM=542,24,1923.104
  564.37  712.25  860.06  971.19 1225.24
River Rch & RM=542,24,1730.859
  566.32  715.08  863.57  975.65 1231.68
River Rch & RM=542,24,1538.615
  571.16  722.09  872.28  986.73 1247.68
River Rch & RM=542,24,1346.371
  574.03  726.26  877.46  993.33 1257.21
Boundary for River Rch & Prof#=542,24,1
Up Type= 0
Dn Type= 2
Boundary for River Rch & Prof#=542,24,2
Up Type= 0
Dn Type= 2
Boundary for River Rch & Prof#=542,24,2
Up Type= 0
Dn Type= 2
Boundary for River Rch & Prof#=542,24,2
Up Type= 0
Dn Type= 2
Boundary for River Rch & Prof#=542,24,2
Up Type= 0
Dn Type= 2

--- 542_ras.g01 (geometry) ---

Geom Title=542
Program Version=4.10

River Reach=542,24
Reach XY= 30
1271549.42611104 623965.118776431271779.33203992623329.615195983
1271850.16534835623192.9485678081271881.83199998623000.448624035
1272030.16528326622785.4486835221272038.49860935 622621.28206537
1272075.99859581622538.7820887551272183.49856379622527.948755503
1272245.99854006 622346.282140941272488.81164375622311.866874587
1272723.81157083622191.0335702641272940.47816837622013.533616613
1272981.31148729621931.8669729751273127.97810669621797.700341898
1273231.31140906621781.0336771341273372.14469847621700.200363647
1273484.64466533621701.8670265141273619.64462384621646.033705804
1273652.14461306621604.3670505681273659.64460841621521.867074855
 1273751.3112451621423.5337680241273764.64457175621329.367128926
1273797.14456116621295.2004714691273797.14455981621249.367151714
1273755.47790402621201.0338339411273777.97789486621114.367192381
1273765.31235604620996.5574698151273852.81232648620869.057505111
 1273969.4789586620864.0575031941274018.64560938620817.390848957

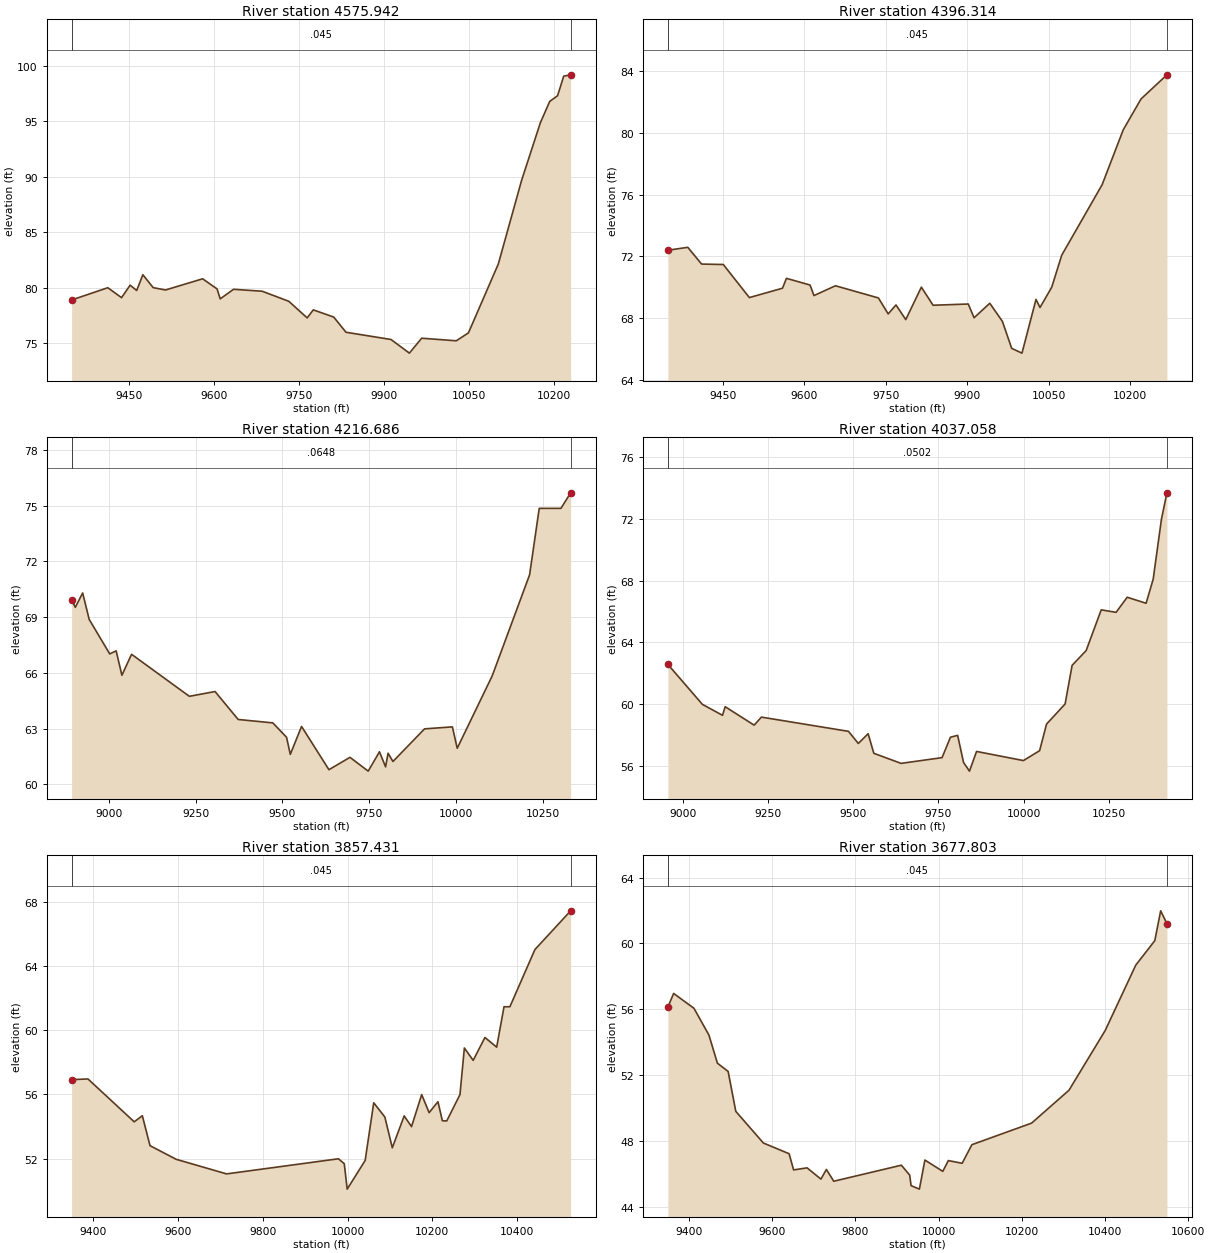
Type RM Length L Ch R = 1 ,4575.942,179.627800,179.627800,179.627800
XS GIS Cut Line= 6
 1272139.3341386624240.3286862371271880.55937856624115.965307578
1271550.74679285623964.6130100791271548.92034468 623963.79809466
1271529.92219684623955.338486865 1271338.6856156623872.471096575
#Sta/Elev= 30
 9349.0178.882479412.947 79.98929437.17279.092379452.32180.218719463.90779.73914
9474.827 81.15989493.02879.996769514.86879.784519580.38980.794519605.86979.88029
9611.37978.983989634.98979.846699685.53679.671639732.46378.764879764.95177.26604
9775.78177.990659811.879 77.33979833.538  75.9699912.95375.317459945.44174.08612
  9967.175.4317110028.2975.1992610049.7475.9168110102.4582.1263710143.7189.70086
10176.7294.8763410193.2296.8025610207.0797.3134310217.9899.0850210230.2299.20152
#Mann= 3 , 0 , 0
 9349.01   0.045       0 9349.01   0.045       010230.22   0.045       0
#XS Ineff= 2 , 0
       09902.327                       0
Bank Sta=9349.01,10230.22
Exp/Cntr=0.3,0.1

Type RM Length L Ch R = 1 ,4396.314,179.627700,179.627700,179.627700
XS GIS Cut Line= 6
1272216.51102239 624076.31617181 1271990.0259766623968.552315563
1271685.33907115623831.9607110171271598.65647772623786.923632145
1271554.57042721623766.6557930411271380.50527647623695.834586069
#Sta/Elev= 30
9349.01772.392629385.67172.582059411.10471.49603 9451.0771.467329499.05569.32354
9560.06969.929289567.33670.571359610.81970.13545 9618.0169.45423 9657.5670.08883
9736.65969.299629754.63768.263759769.01868.845089786.99567.895549815.75969.99759
9837.33168.825539902.04968.906359912.836 68.01449941.71968.954549964.93367.78242
9982.07366.03008   1000165.7216110026.8569.2052910034.2168.6803110055.8770.00217
10074.1872.0697310148.5376.6375810187.5680.2072510220.25 82.203210267.8983.76514
#Mann= 3 , 0 , 0
9349.017   0.045       09349.017   0.045       010267.89   0.045       0
#XS Ineff= 2 , 0
       09915.837                       0
Bank Sta=9349.017,10267.89
Exp/Cntr=0.3,0.1

Type RM Length L Ch R = 1 ,4216.686,179.627700,179.627700,179.627700
XS GIS Cut Line= 6
 1272690.8593398624102.0993930551272181.02819905623835.066171259
1272060.74672005623780.3930151461271864.15008572623698.573934704
1271735.71390411 623650.394129471271376.16885364623523.823147193
#Sta/Elev= 30
 8892.1869.941268902.83969.531918924.053 70.30418942.80868.883599002.066  67.025
9020.58467.18998 9037.1965.875839065.02867.00438 9231.6964.743719305.76265.00094
9372.427 63.49779472.29863.31427 9511.9462.540549522.752 61.62099555.18763.12242
9634.14560.795949694.83361.460899747.36860.718639779.826 61.75889797.52560.94856
9804.60561.681799818.70461.23663 9909.8162.992739990.13163.0997310004.0561.94873
10104.9165.8434210212.7271.2810110240.5474.8562810303.1474.8577310331.1475.69279
#Mann= 3 , 0 , 0
 8892.18  0.0648       0 8892.18  0.0648       010331.14  0.0648       0
#XS Ineff= 2 , 0
       0 9920.58                       0
Bank Sta=8892.18,10331.14
Exp/Cntr=0.3,0.1

Type RM Length L Ch R = 1 ,4037.058,179.627700,179.627700,179.627700
XS GIS Cut Line= 6
1272680.44267315623927.6202263831272245.91856378623656.465609878
1272125.63440174 623601.803571031271813.64566648623483.282335013
1271638.16050673623434.8323818741271347.94294015623340.409554616
#Sta/Elev= 30
8955.54362.562129056.71959.973349116.01359.260489123.74859.819479208.82758.62304
9230.24159.143499485.93558.220849514.76557.434739543.59558.066079560.33756.79637
9640.38556.142869760.69656.51567 9785.3357.839159806.44657.96009 9823.8756.19758
9841.19655.640189861.98756.916479999.53756.3244510047.1456.9664110067.5458.69209
10121.9959.99397 10142.662.5018910183.82 63.459210228.0566.1005810271.6865.94061
10304.3966.9189410359.8466.5286310380.6368.0870910404.89  71.97710421.0173.69173
#Mann= 3 , 0 , 0
8955.543  0.0502       08955.543  0.0502       010421.01  0.0502       0
#XS Ineff= 2 , 0
       09910.543        10131.92       0
Bank Sta=8955.543,10421.01
Exp/Cntr=0.3,0.1

Type RM Length L Ch R = 1 ,3857.431,179.627700,179.627700,179.627700
XS GIS Cut Line= 6
1272401.47124687623559.9806396511272171.50764129623447.659217969
1271829.87562057623307.8292146031271793.94529873623297.436454505
1271690.51198351623253.8616591841271310.42297873623122.251401976
#Sta/Elev= 30
9349.081  56.9169387.63756.959219496.76254.28699 9515.8754.667219533.97552.80285
9595.53151.952959714.63651.04217 9978.4851.984429992.19951.676249999.05750.09287
10041.46 51.879510061.67 55.4732 10087.954.5865110105.4952.6689710133.4954.65527
10150.8153.9870510174.7855.9836910192.3754.8580310213.1455.5389210223.5354.35561
10233.9254.3424310265.09 55.986510275.4858.8888410296.2658.1172110323.97  59.543
10351.6758.9409510368.9961.4579410382.8461.4589210441.8865.0235910526.1867.43637
#Mann= 3 , 0 , 0
9349.081   0.045       09349.081   0.045       010526.18   0.045       0
#XS Ineff= 2 , 0
       09932.259        10073.45       0
Bank Sta=9349.081,10526.18
Exp/Cntr=0.3,0.1

Type RM Length L Ch R = 1 ,3677.803,179.627800,179.627800,179.627800
XS GIS Cut Line= 6
1272444.83067855623374.2902757531272223.50621778623256.177662313
1272045.21075052623179.1780611131271940.83721867623147.202177525
1271680.54272431623095.6161180441271322.98535812622968.356914058
#Sta/Elev= 30
9349.06156.136419362.89356.966329411.75156.064369447.73654.43961 9468.1252.73147
9493.91652.231239512.34249.806499578.67447.884259640.49547.23433 9651.3346.25108
9683.71446.376149716.99245.692999730.133 46.27899747.81945.563749910.34846.53725
9930.40545.935079933.74845.296729953.71845.084729966.95546.8503510010.0146.16326
 10023.346.8172710056.5146.65386   1008047.7841610223.3549.0902610313.3451.08865
10400.3854.7139310473.9558.6864310519.6360.1675410533.7661.98165 10548.861.20219
#Mann= 3 , 0 , 0
9349.061   0.045       09349.061   0.045       0 10548.8   0.045       0
#XS Ineff= 2 , 0
       09920.566        10036.49       0
Bank Sta=9349.061,10548.8
Exp/Cntr=0.3,0.1

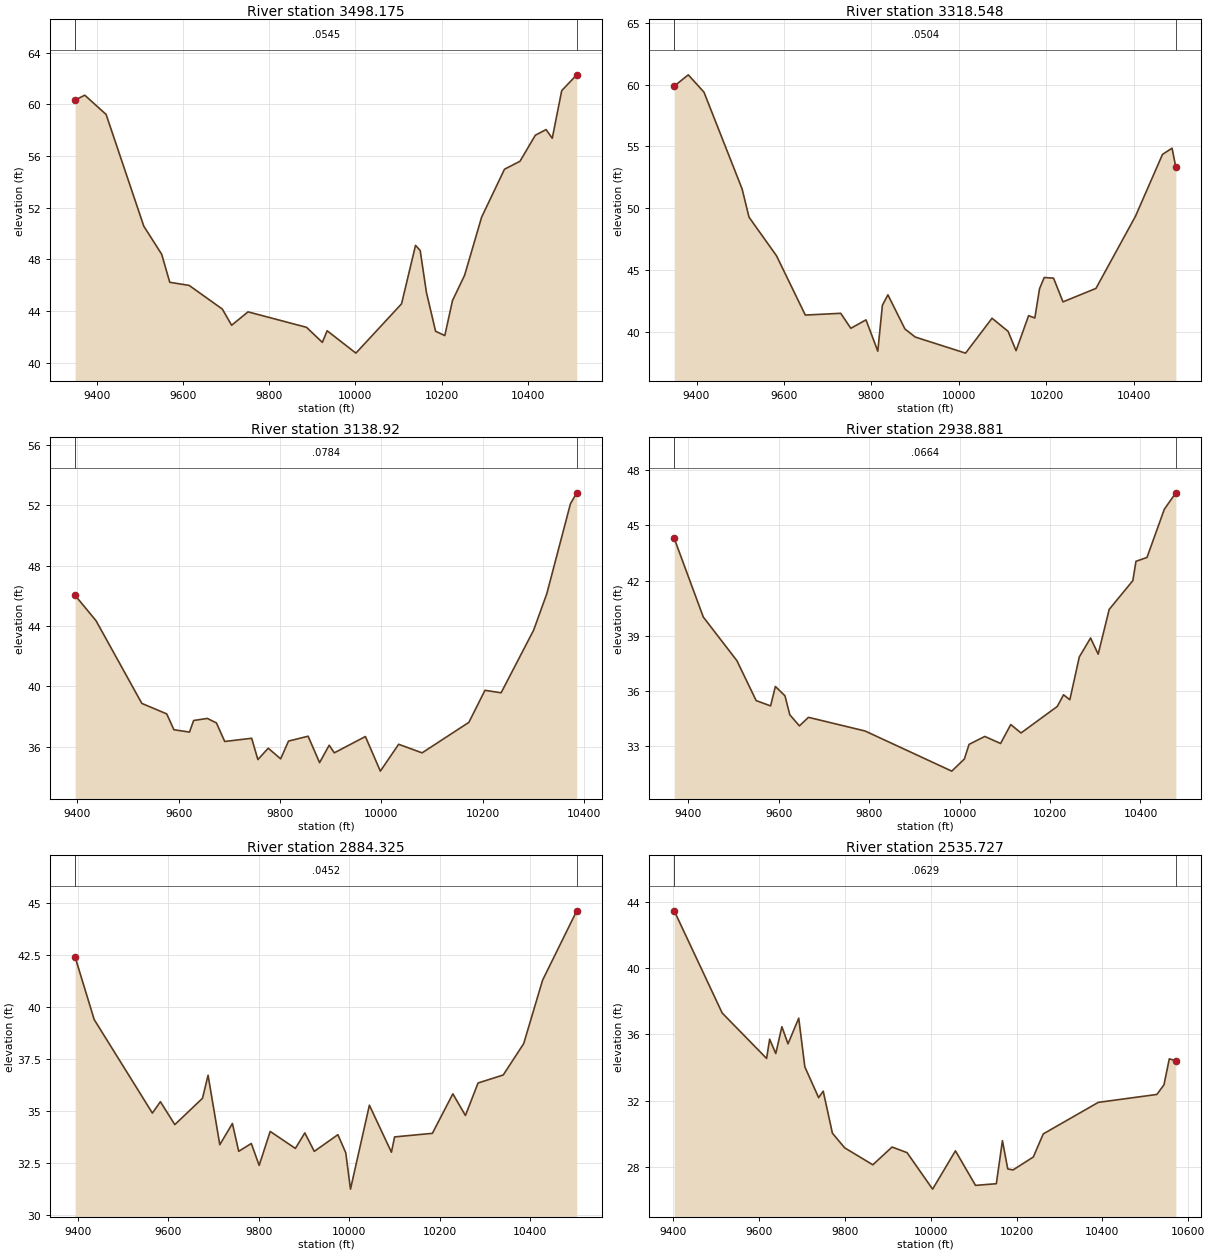
Type RM Length L Ch R = 1 ,3498.175,179.627700,179.627700,179.627700
XS GIS Cut Line= 6
1272474.62582359623272.1747046861272373.05483222623210.568269879
1272258.12637648623145.5974883591271849.04981652622935.325001687
1271754.70541072622892.0190683311271432.65979466 622754.17616868
#Sta/Elev= 30
9349.01560.328649371.44860.702169421.00759.211469508.52350.56797 9549.9848.40082
9568.82446.22786 9613.8345.986939690.87244.155339712.45842.904769750.58243.94015
9886.43842.743279923.156 41.57869934.24442.4790710001.0340.7472810107.0544.55972
10139.54 49.084610150.3748.6857510164.7945.4525210186.1342.4372610207.5442.10707
10225.3544.8117810253.4946.7676610293.0351.2671910346.1254.9739510382.0955.58983
10417.7257.6040410442.6658.0427310457.0457.3708210479.0661.0575510513.9362.27736
#Mann= 3 , 0 , 0
9349.015  0.0545       09349.015  0.0545       010513.93  0.0545       0
#XS Ineff= 2 , 0
       09880.968        10061.75       0
Bank Sta=9349.015,10513.93
Exp/Cntr=0.3,0.1

Type RM Length L Ch R = 1 ,3318.548,179.627700,179.627700,179.627700
XS GIS Cut Line= 6
1272544.50546476623177.5884412081272334.95526263623036.373015091
1272071.08941326622872.1401623041271983.26674438622796.574001327
1271952.30702922   622775.3288051271562.08719841622595.900186628
#Sta/Elev= 30
9349.06459.876779381.21860.791529417.11559.388119504.33451.556469520.04449.28036
9582.88346.157499648.748 41.36219729.67241.504279752.79340.290369787.47540.97445
9814.44938.44095  9824.942.14916 9837.5742.997589876.51440.234689899.94739.58477
10015.0838.28355 10075.641.1041110112.3140.0453310130.5138.4811210159.13 41.3132
10173.4341.1273910184.1643.4898510194.8944.3981210216.2244.3487910237.8142.42958
10313.1443.5172510403.3949.3482810465.2854.3575110487.1254.8567910495.7953.31452
#Mann= 3 , 0 , 0
9349.064  0.0504       09349.064  0.0504       010495.79  0.0504       0
#XS Ineff= 2 , 0
       09860.576         10078.1       0
Bank Sta=9349.064,10495.79
Exp/Cntr=0.3,0.1

Type RM Length L Ch R = 1 , 3138.92,200.039300,200.039300,200.039300
XS GIS Cut Line= 6
1272548.20887685622957.0762449061272152.56820497622672.313315138
1272100.40702647622651.5410228971271999.48747328622649.167566746
1271911.88593426 622632.569342271271676.68109906622533.465133801
#Sta/Elev= 30
9395.68146.033499436.90944.358749527.34338.879019576.42438.184629590.74737.13378
9621.415 36.97919629.59537.747389656.67837.883489674.58737.585159690.94736.35681
9744.11936.570099756.38935.15931 9776.8435.91267 9801.2935.206759816.85536.38385
9855.49136.705399878.17434.956739897.06536.108149907.23435.605179968.56336.68448
9998.09234.3930510034.1936.1709310080.4735.6035110172.76 37.622310204.5539.74535
10236.4539.58355 10300.643.7302410326.5446.1375710373.2952.10684 10385.752.82699
#Mann= 3 , 0 , 0
9395.681  0.0784       09395.681  0.0784       0 10385.7  0.0784       0
#XS Ineff= 2 , 0
       09840.876        10083.98       0
Bank Sta=9395.681,10385.7
Exp/Cntr=0.3,0.1

Type RM Length L Ch R = 1 ,2938.881,54.555600,54.555600,54.555600
XS GIS Cut Line= 3
 1272594.2158213622909.9842310251272489.24570027622651.830477014
1271706.62901577622373.959925473
#Sta/Elev= 30
9369.00944.299799433.29140.020759507.66637.643849550.16735.474839582.04235.18516
9592.66736.242849613.91735.734669624.54234.704579645.79234.098879665.85534.56384
9791.18933.818829982.67131.6371810010.5232.2958410020.9733.0933510055.7833.52421
 10090.633.1404810113.1134.1695310135.8633.7136310215.9335.1550410229.8635.78996
10243.7835.5201510264.6737.8468410289.6138.8789610306.4538.0010410330.82 40.4352
10383.04 41.998810390.0143.0505910414.3843.2613210452.6745.8826410478.17 46.7761
#Mann= 3 , 0 , 0
9369.009  0.0664       09369.009  0.0664       010478.17  0.0664       0
#XS Ineff= 2 , 0
       09917.073        10161.16       0
Bank Sta=9369.009,10478.17
Exp/Cntr=0.3,0.1

Type RM Length L Ch R = 1 ,2884.325,348.598300,348.598300,348.598300
XS GIS Cut Line= 3
1272609.40679352622870.9217310251272504.43667249622612.767977014
  1271721.819988622334.897425473
#Sta/Elev= 30
9393.54142.422749435.72639.416159564.40534.918549582.11335.467179613.98934.36438
9675.17335.62991  9687.536.738989713.46933.398499741.32134.417559755.24733.08085
9783.09933.455699800.507 32.40399824.87734.036959880.58133.21947 9901.4733.96598
9922.35933.078479974.58133.880079991.98933.0070110002.4331.2622110044.2135.29716
10092.9533.0368210099.9233.7734510183.4733.9453110228.7335.8437610256.5834.80343
10284.4336.3650210340.14 36.7511 10385.4 38.258710427.1841.31102 10502.744.64494
#Mann= 3 , 0 , 0
9393.541  0.0452       09393.541  0.0452       0 10502.7  0.0452       0
#XS Ineff= 2 , 0
       09950.301           10184       0
Bank Sta=9393.541,10502.7
Exp/Cntr=0.3,0.1

Type RM Length L Ch R = 1 ,2535.727,228.134500,228.134500,228.134500
XS GIS Cut Line= 4
1272650.72623795622877.8227726821272453.24359906622415.583189338
1272396.13750246622262.1105547551271997.42762685621955.687356025
#Sta/Elev= 30
9402.05243.448799513.88937.289269617.35334.552299624.48835.713259638.75934.84718
 9653.0336.464129667.30135.431199692.27536.979929706.54634.042399738.65532.18979
9749.35832.580989770.765  30.0489799.306 29.16489864.998 28.14229909.80729.21208
9944.81328.8748110004.3226.6750510057.5428.9834410104.4226.9000310152.8727.00156
 10167.1 29.595110179.5227.8923810191.9327.8328310239.0228.6110410262.2730.00309
10390.5431.9041210527.0932.3815710543.6432.9627310556.0634.5264310571.3234.41911
#Mann= 3 , 0 , 0
9402.052  0.0629       09402.052  0.0629       010571.32  0.0629       0
#XS Ineff= 2 , 0
       09939.442        10214.13       0
Bank Sta=9402.052,10571.32
Exp/Cntr=0.3,0.1

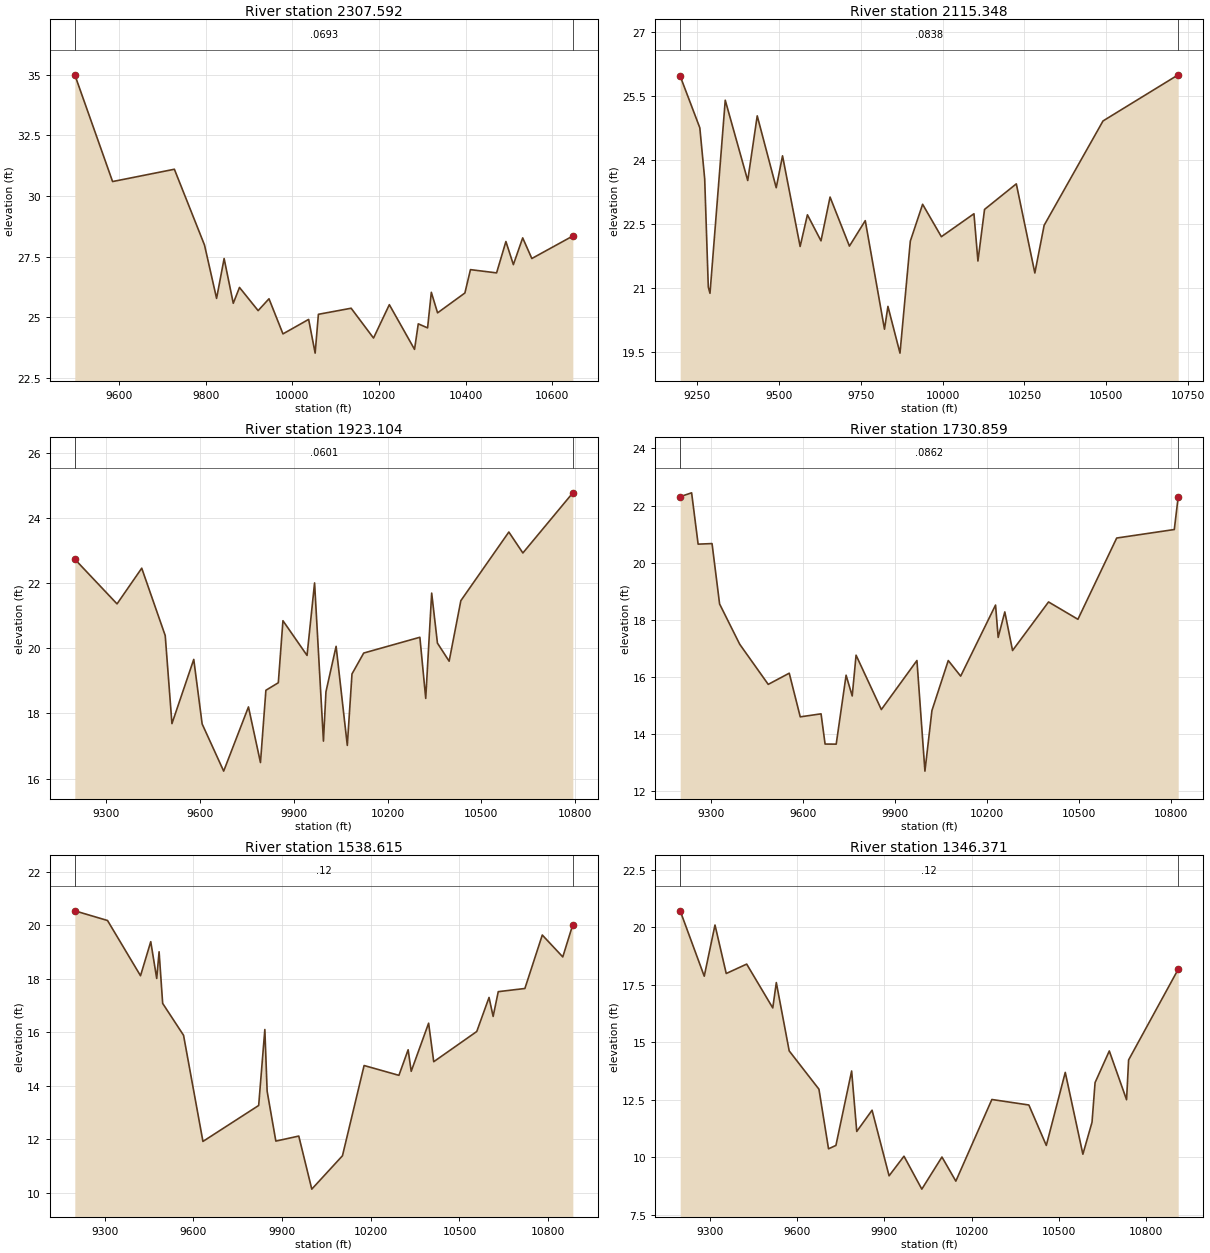
Type RM Length L Ch R = 1 ,2307.592,192.244200,192.244200,192.244200
XS GIS Cut Line= 6
1272809.14637685622719.4026338161272689.78873798622383.031106025
   1272634.86021622258.8418447081272630.03784874622249.234507531
 1272582.4970713622164.020689353 1272164.0942935621808.117911577
#Sta/Elev= 30
9497.53434.997419584.77730.596879727.50831.104129797.134  27.9789824.98425.77964
 9842.3927.422289863.54625.577879877.89626.231349920.94525.275349946.05725.76426
9978.344 24.315710037.6424.9136310052.6723.5228210060.1825.12341 10135.825.37377
10187.4824.1443210224.0525.5202410282.2423.6775410290.8624.7300910312.3924.56338
10321.0126.0299910335.45 25.183310398.5426.0021310411.4126.9653810471.7626.83127
 10493.328.1246710510.5327.1721710532.0628.2742610553.1927.4236710647.8828.35207
#Mann= 3 , 0 , 0
9497.534  0.0693       09497.534  0.0693       010647.88  0.0693       0
#XS Ineff= 2 , 0
       09925.303        10127.99       0
Bank Sta=9497.534,10647.88
Exp/Cntr=0.3,0.1

Type RM Length L Ch R = 1 ,2115.348,192.244300,192.244300,192.244300
XS GIS Cut Line= 6
1273284.39636189622754.0682811141273156.84800449622598.502823979
1272910.71215349622279.1419221611272806.43598002622155.173850685
1272742.33932611622100.1736979041272198.81651574621709.159578249
#Sta/Elev= 30
9199.07125.971459258.99524.760459273.85523.565069284.86821.031019290.04220.88459
9336.61325.407239405.25423.52611 9434.2525.04092 9492.2423.357059511.512 24.1046
9565.25721.98151 9587.5122.723429628.93222.113469656.62323.138849715.74221.99008
9764.11222.586379822.80320.04397 9833.32 20.57799870.12819.483339901.67822.10674
9939.19622.969569996.45222.2104210095.9422.7476510108.0721.6406610128.2822.84938
10225.2823.4484310281.8621.3607310310.2522.4775610490.02 24.921910719.5826.00185
#Mann= 3 , 0 , 0
9199.071  0.0838       09199.071  0.0838       010719.58  0.0838       0
#XS Ineff= 2 , 0
       09933.356        10114.55       0
Bank Sta=9199.071,10719.58
Exp/Cntr=0.3,0.1

Type RM Length L Ch R = 1 ,1923.104,192.244200,192.244200,192.244200
XS GIS Cut Line= 6
1273435.60635272622640.7490317231273079.85295486622189.162131071
1273024.02078035622124.6506247971272947.75575101622042.535068214
 1272915.1214053621998.5763321371272243.52137688621628.430411577
#Sta/Elev= 30
 9199.0622.73941 9334.1821.366549413.239 22.46339488.42720.39154 9509.9117.68629
9579.72719.66034 9606.58 17.6769 9675.49 16.22719754.81618.200169793.24916.49135
9810.60518.711919850.35318.942899865.15920.849729942.29619.782959966.40122.01074
9994.78717.1491510002.8418.6670410035.3120.0625710071.1617.0183510086.1519.21359
10123.6719.8558710303.4220.3407510322.1518.4621310341.1721.6977410359.6120.16183
10397.0819.6047910434.54 21.465210588.1323.5746710633.08 22.931410792.9624.77955
#Mann= 3 , 0 , 0
 9199.06  0.0601       0 9199.06  0.0601       010792.96  0.0601       0
#XS Ineff= 2 , 0
       09943.329        10159.95       0
Bank Sta=9199.06,10792.96
Exp/Cntr=0.3,0.1

Type RM Length L Ch R = 1 ,1730.859,192.244300,192.244300,192.244300
XS GIS Cut Line= 6
1273541.70300436622512.2459447091273135.14259356621961.910107076
1273086.90964553621909.7993561631273003.14812604621838.411055803
1272920.60471019621775.9998560251272325.98665461 621502.56235601
#Sta/Elev= 30
9199.035 22.3107 9236.2622.444759257.46220.647929302.83220.667569327.47718.55247
9392.88917.146289486.03215.737889554.52316.129369590.39914.600489658.23114.70648
9671.36113.64847 9707.6213.645579739.85116.058649759.77215.331789772.36716.76037
9854.75514.856559970.78416.573749996.84712.7004810019.6314.8200210072.9116.57308
10113.3316.0263110227.0318.5153710235.5617.3825410257.2318.2754310282.5116.92348
10399.7918.6237610495.5618.0165210621.9520.8617410809.7321.1599210822.5322.30696
#Mann= 3 , 0 , 0
9199.035  0.0862       09199.035  0.0862       010822.53  0.0862       0
#XS Ineff= 2 , 0
       09931.667        10150.93       0
Bank Sta=9199.035,10822.53
Exp/Cntr=0.3,0.1

Type RM Length L Ch R = 1 ,1538.615,192.244200,192.244200,192.244200
XS GIS Cut Line= 6
1273616.27557832622468.8201668711273438.36797228622229.285531133
1273291.22295001621994.5650247481273226.09635863621864.365062624
1273164.52522126621672.7800554191272443.17415464621428.777633801
#Sta/Elev= 30
9199.08820.545759309.70420.183939421.29718.117969455.90319.391889476.05118.01613
 9484.1119.014199496.199 17.08349566.80915.891469632.40311.920649820.89513.26565
9841.74216.106759849.52613.796069878.95611.933589956.493 12.121410000.5210.13708
10104.2311.3843410177.4314.7603410295.1814.3930110326.3515.3492610336.7414.54411
10395.6216.3429910412.9414.90235 10558.416.0320810599.9717.3057910613.8216.59637
10631.1417.5224410721.1917.6409910780.0619.6407910849.3318.8219610883.3620.03364
#Mann= 3 , 0 , 0
9199.088    0.12       09199.088    0.12       010883.36    0.12       0
#XS Ineff= 2 , 0
       09918.763        10116.51       0
Bank Sta=9199.088,10883.36
Exp/Cntr=0.3,0.1

Type RM Length L Ch R = 1 ,1346.371,192.244300,192.244300,192.244300
XS GIS Cut Line= 6
1273753.83111924622395.4957637041273523.55638593622075.915702567
1273441.81759733621917.4765309241273358.97276577621656.642217144
 1273289.5283213621576.347078249 1272584.2331824621300.739439353
#Sta/Elev= 30
 9199.1120.707549281.72217.869549318.63920.090859357.27617.98627 9427.5118.39407
9517.11616.491529529.28717.59225 9573.5614.625459675.73312.96239 9708.6510.37448
9734.06710.521039788.01713.752369805.61711.127439858.19312.050259916.6629.201153
9967.86710.05351 10029.18.62360210098.2810.0176810145.998.97035510269.7312.51557
10396.86 12.276110456.7610.5208710521.8713.6916210582.4110.1397710613.82 11.5286
10624.2913.2488810673.1514.6229910732.4912.5046310739.4714.23231 10909.918.17066
#Mann= 3 , 0 , 0
 9199.11    0.12       0 9199.11    0.12       0 10909.9    0.12       0
#XS Ineff= 2 , 0
       09884.559        10119.75       0
Bank Sta=9199.11,10909.9
Exp/Cntr=0.3,0.1

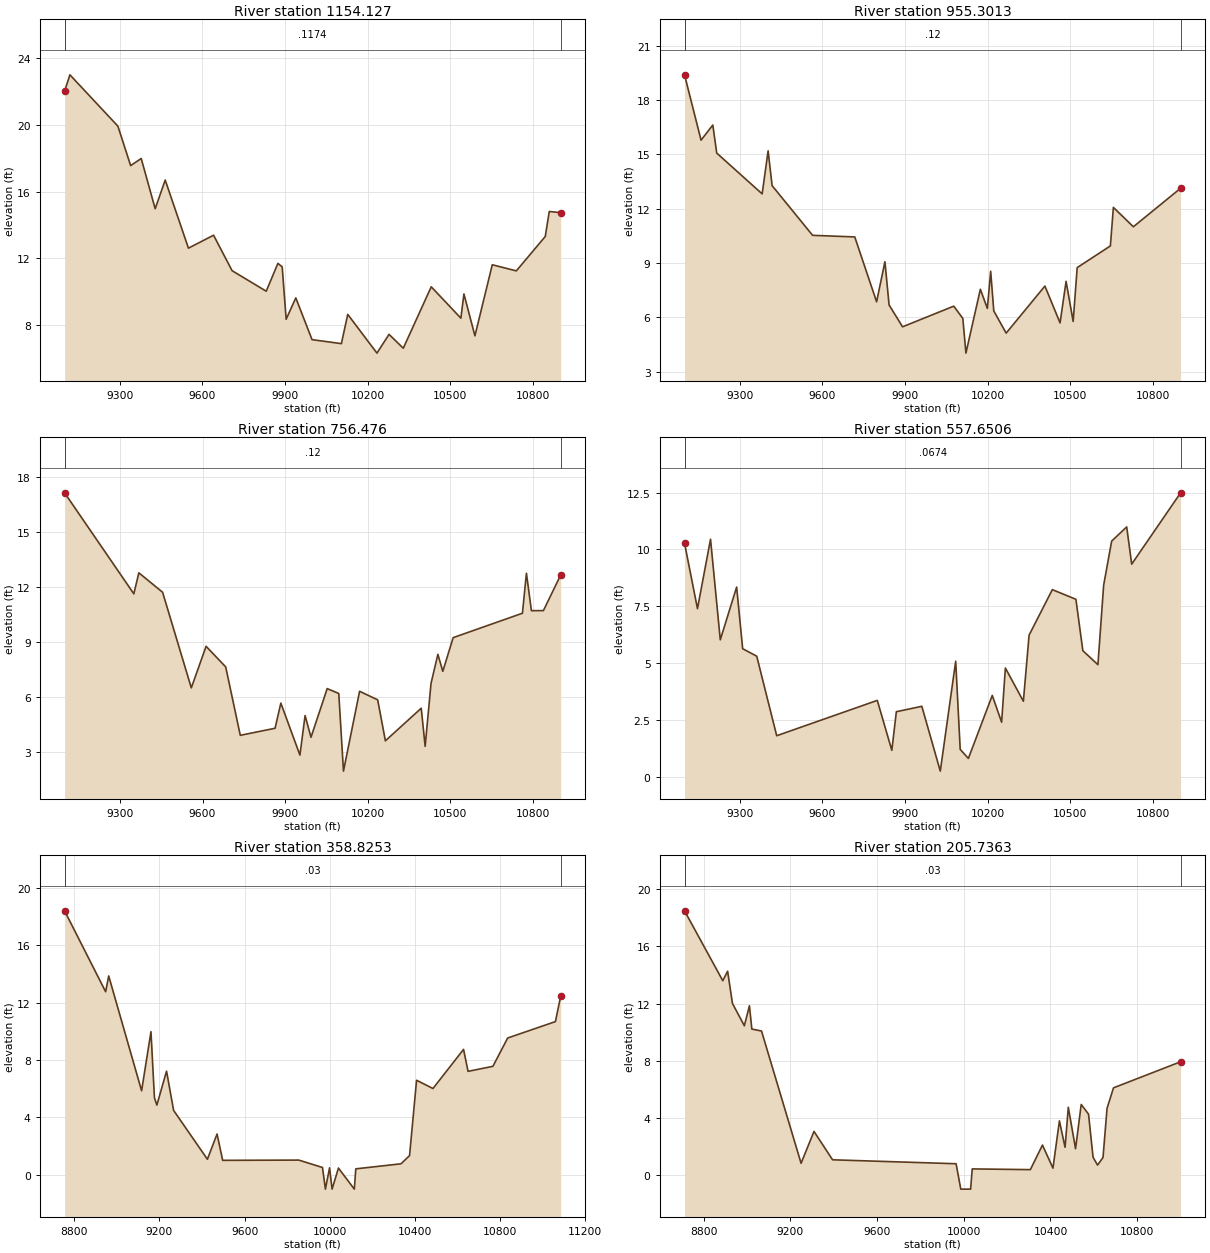
Type RM Length L Ch R = 1 ,1154.127,198.825300,198.825300,198.825300
XS GIS Cut Line= 6
1274301.40164017622154.3097445571273810.76020233621938.891335679
1273636.74386587621800.3744615661273529.42645212621625.521509942
1273417.02471988 621524.676559651272815.20936091621203.252179889
#Sta/Elev= 30
9099.14622.027129118.46823.00732 9292.7919.923939338.99917.555669377.43417.98186
9428.17814.964419464.57216.688969548.98112.598319640.23713.374299707.475 11.2456
9831.46710.01253 9873.9811.684829889.46911.472759903.8678.3279899938.9089.612171
9997.8377.10406310104.476.86337610127.568.61996910233.62 6.2941510277.52 7.42056
10329.276.58844710430.8410.2768810538.528.39293910549.549.84847810589.517.332862
10652.4711.6003910739.8511.2339910844.9713.2998110859.46 14.798610900.8914.73106
#Mann= 3 , 0 , 0
9099.146  0.1174       09099.146  0.1174       010900.89  0.1174       0
#XS Ineff= 2 , 0
       09928.059        10197.81       0
Bank Sta=9099.146,10900.89
Exp/Cntr=0.3,0.1

Type RM Length L Ch R = 1 ,955.3013,198.825300,198.825300,198.825300
XS GIS Cut Line= 6
1274463.16917865621930.2093969141274087.18812882621761.715059335
1273716.00546889621556.6707537521273601.71535718 621506.92324133
1273287.01657188621336.810740944 1272851.8777682621126.779340806
#Sta/Elev= 30
9099.04719.390489159.06715.785759201.75716.620579215.98715.07213 9380.9812.82143
9402.62815.194999417.167 13.2753 9564.1710.533749717.36210.445399796.7126.865926
9826.9419.0770049842.0556.6909819890.9885.48534810076.936.62519410109.875.949084
10121.124.033396 10173.67.55616910198.966.501242 10211.18.54928510222.346.361432
10267.335.13688210408.067.73463210463.075.70275710485.027.99377510510.645.781835
10525.288.75164810645.879.94951710656.77 12.075410729.3911.0059410900.9613.13085
#Mann= 3 , 0 , 0
9099.047    0.12       09099.047    0.12       010900.96    0.12       0
#XS Ineff= 2 , 0
       09758.123        10191.38       0
Bank Sta=9099.047,10900.96
Exp/Cntr=0.3,0.1

Type RM Length L Ch R = 1 , 756.476,198.825400,198.825400,198.825400
XS GIS Cut Line= 6
 1274588.3415588621709.833033462 1273958.6820461621434.789505508
1273800.03530278621378.1483920351273631.15047142621340.280831099
1273408.53038728621260.948624308 1272920.6510546621038.174417097
#Sta/Elev= 30
9099.039 17.14289350.52611.636219368.75812.780549455.04111.721969559.2996.509368
9613.0118.7742089684.2297.6513779737.2153.9224019863.5534.3061879884.5415.678738
9953.8382.8442599972.5954.9996359994.0693.81555910052.866.46907510094.946.202894
   10112 1.9698310170.576.32274510236.27 5.8563910264.263.62212510394.455.399425
10408.683.32128510430.036.75205910454.938.33731110472.837.41088910510.429.247139
10762.0310.5782110776.5412.7578710794.6810.71776 10838.210.7208710900.9212.65994
#Mann= 3 , 0 , 0
9099.039    0.12       09099.039    0.12       010900.92    0.12       0
#XS Ineff= 2 , 0
       09806.354        10201.12       0
Bank Sta=9099.039,10900.92
Exp/Cntr=0.3,0.1

Type RM Length L Ch R = 1 ,557.6506,198.825300,198.825300,198.825300
XS GIS Cut Line= 6
1274597.71392918621463.6334980581274048.68433345621213.605462724
1273905.49514899621185.3109424231273690.13289876621210.963102466
1273532.35830736621189.3760370791272912.49156767620926.198715713
#Sta/Elev= 30
9099.12210.274459146.1087.3908489193.529 10.44679228.9756.0200589288.3728.342737
9310.2595.6294479361.3225.2999589433.8841.8001319799.2083.3548859852.0261.157093
9868.4312.8571479960.9773.09426510028.040.24234210083.965.07770610100.371.199658
10130.040.80026310216.813.57417610250.792.39582210264.434.77969910329.773.317571
10350.556.22574310434.988.22869210520.627.80315610545.815.54162510600.544.926361
 10621.48.42554910650.4410.3640710705.0610.9890310723.269.35139610900.87 12.4888
#Mann= 3 , 0 , 0
9099.122  0.0674       09099.122  0.0674       010900.87  0.0674       0
#XS Ineff= 2 , 0
       09790.829        10194.52       0
Bank Sta=9099.122,10900.87
Exp/Cntr=0.3,0.1

Type RM Length L Ch R = 1 ,358.8253,153.089000,153.089000,153.089000
XS GIS Cut Line= 6
1274866.96249378621580.7090574061273995.68628249621086.958930671
1273914.53977254621049.0042152551273591.43165645 620963.75206551
1273344.63351735620851.6028178041272757.58749378620614.997251868
#Sta/Elev= 30
8754.12618.410838947.01112.766998961.33513.870699115.9475.8606459159.9529.981098
9176.2835.3715049187.5964.862153 9233.157.2265629266.4224.4899129425.171 1.08341
9470.4232.8439339496.8211.0088699854.4721.0259469965.7790.511371 9979.51  -0.999
    99990.48784710010.91  -0.99910040.830.46960810115.37  -0.99910122.310.414927
10334.770.76756910374.89 1.3414310407.816.59421710484.876.01818510628.588.746726
 10649.87.21505810766.537.56659210835.939.54035311060.1310.6844611084.8612.44827
#Mann= 3 , 0 , 0
8754.126    0.03       08754.126    0.03       011084.86    0.03       0
#XS Ineff= 2 , 0
       09748.415        10181.88       0
Bank Sta=8754.126,11084.86
Exp/Cntr=0.3,0.1

Type RM Length L Ch R = 1 ,205.7363,0.000000,0.000000,0.000000
XS GIS Cut Line= 2
1274979.90013841621491.5344335731272963.84111065620408.635128006
#Sta/Elev= 30
8711.92918.491078888.34713.596618910.69214.260828933.03712.004288987.91710.44135
9011.244 11.84229022.41710.212269067.10710.071899249.5910.8114449309.1783.042758
9394.8341.0546939964.6310.7790119986.322  -0.99910031.67  -0.99910039.110.416837
10307.25 0.3657410363.122.08609710411.530.47153210441.32 3.7805210467.391.930579
10482.29 4.7333410515.811.83255810541.884.92952410575.66 4.2503910596.461.234133
10617.260.68443110642.431.21472710661.054.65676810690.846.09490111000.417.919349
#Mann= 3 , 0 , 0
8711.929    0.03       08711.929    0.03       011000.41    0.03       0
#XS Ineff= 2 , 0
       09724.126        10364.78       0
Bank Sta=8711.929,11000.41
Exp/Cntr=0.3,0.1